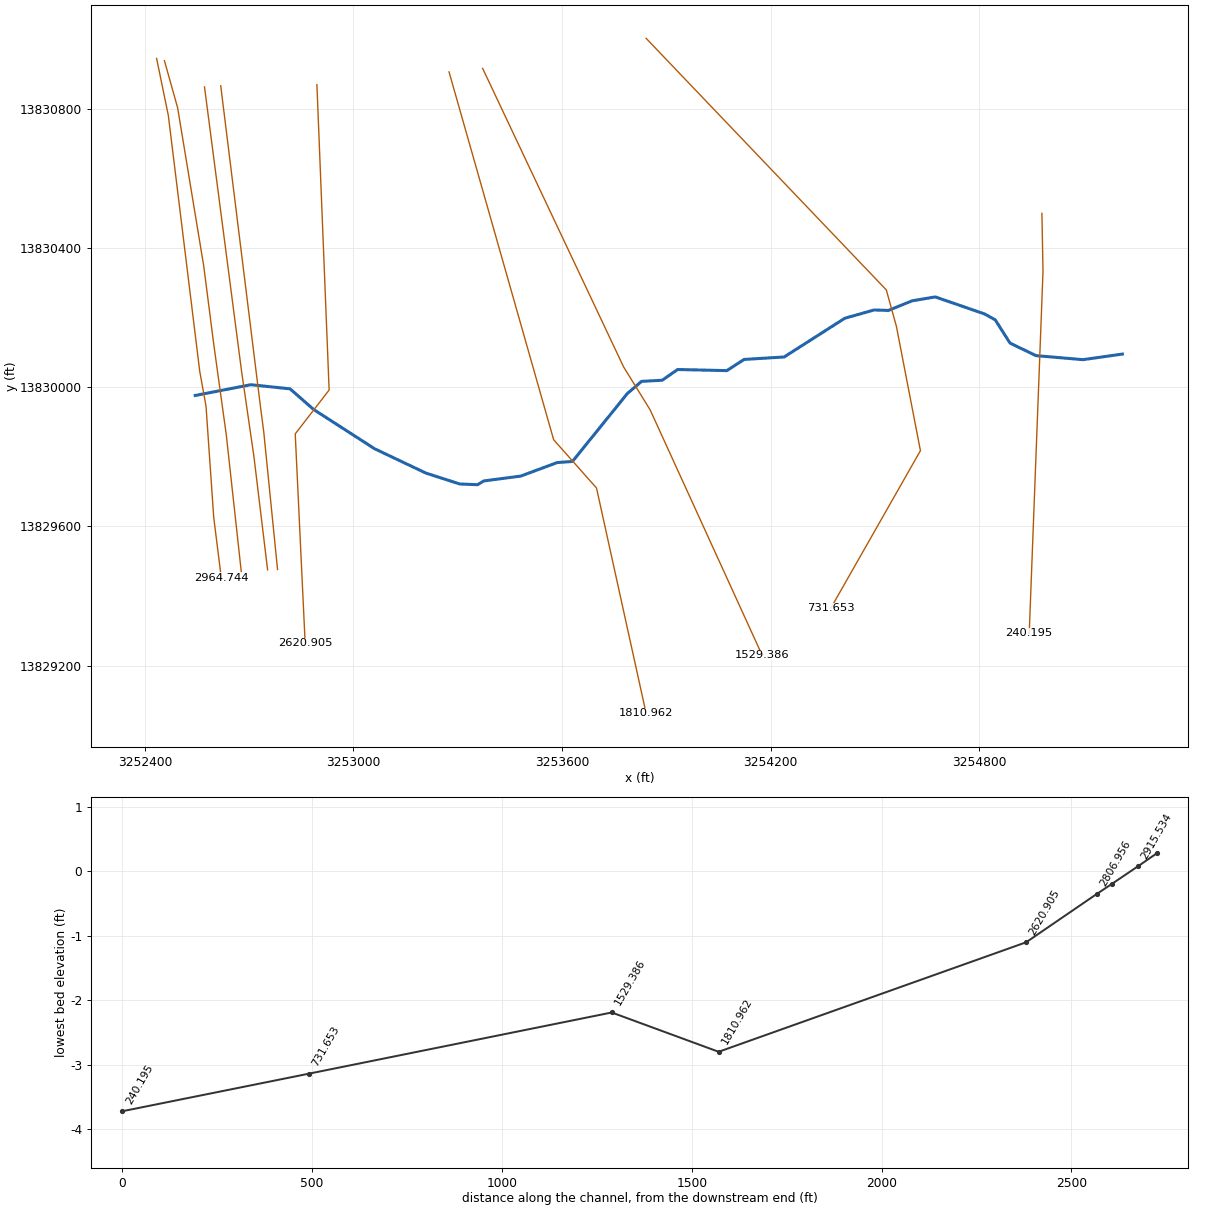
--- Q101-00-00.prj (project) ---

Proj Title=Q101-00-00
Current Plan=p05
Default Exp/Contr=.3,.1
English Units
Geom File=g01
Flow File=f03
Flow File=f04
Plan File=p02
Plan File=p05
Y Axis Title=Elevation
X Axis Title(PF)=Main Channel Distance
X Axis Title(XS)=Station
BEGIN DESCRIPTION:
Cedar Bayou watershed
Pine Gully
HCFCD unit Q 101-00-00
(Flood Hazard, Floodway)Model
10, 2, 1, 0.2% Event
Filename q1010000.prj
Prepared by:  FTN Associates Ltd.   DATE:  May 2003
Reviewed by: 	 DATE:
STATUS (FINAL RAS)
Using the two most downstream cross sections, the slope of the stream was calculated to be 0.00119197 ft/ft.
END DESCRIPTION:
DSS File=dss
DSS Export Rating Curves= 0
DSS Export Rating Curve Sorted= 0
DSS Export Volume Flow Curves= 0
DXF OffsetX= 0
DXF OffsetY= 0
DXF ScaleX= 1
DXF ScaleY= 10

--- Q101-00-00.p05 (plan) ---

Plan Title=Floodway
Version=Version 3.0.1  Mar 2001
Short Identifier=Floodway0607
Geom File=g01
Flow File=f04
Subcritical Flow
K Sum by GR= 0
Std Step Tol= 0.01
Critical Tol= 0.01
Num of Std Step Trials= 20
Max Error Tol= 0.3
Flow Tol Ratio= 0.001
Split Flow NTrial= 30
Split Flow Tol= 0.02
Split Flow Ratio= 0.02
Log Output Level= 0
Friction Slope Method= 1
Unsteady Friction Slope Method= 2
Parabolic Critical Depth
Global Vel Dist= 0 , 0 , 0
Global Log Level= 0
CheckData=True
Encroach Param=-1 ,0,0, 2
Encroach River=Q101-00-00
Encroach Reach=Pine Gully
Encroach Node=2964.744
       1     931    1016
Encroach Node=2915.534
       1     912    1002
Encroach Node=2881.6
       1     912    1002
Encroach Node=2847.691
       1     912    1002
Encroach Node=2806.956
       1     818     913
Encroach Node=2620.905
       1     912     998
Encroach Node=1810.962
       1    1094    1264
Encroach Node=1529.386
       1     950    1137
Encroach Node=731.653
       1     907    1158
Encroach Node=240.195
       1     240     675
Encroach Reach=Q101-00-0002
Encroach Node=2964.744
       1     931    1016
Encroach Node=2915.534
       1     912    1002
Encroach Node=2881.6
       1     912    1002
Encroach Node=2847.691
       1     912    1002
Encroach Node=2806.956
       1     818     913
Encroach Node=2620.905
       1     912     998
Encroach Node=1810.962
       1    1094    1264
Encroach Node=1529.386
       1     950    1137
Encroach Node=731.653
       1     907    1158
Encroach Node=240.195
       1     240     675
Computation Interval=1HOUR
Output Interval=1HOUR
Run HTab= 0
Run UNet= 0
Run PostProcess= 0
UNET Theta= 1
UNET ZTol= 0.02
UNET ZSATol= 0.1
UNET MxIter= 20
UNET MaxInSteps= 20
UNET DtIC= 0
UNET DtMin= 0
UNET MaxCRTS= 20
UNET WFStab= 2
UNET SFStab= 1
UNET WFX= 1
UNET SFX= 1
UNET Convert EG Bridges=-1
UNET Use Existing IB Tables=-1
Instantaneous Interval=1HOUR
DSS File=dss
Write IC File= 0
Write Velocity= 0
Write Detailed= 0

--- Q101-00-00.p02 (plan) ---

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Plan Title=FEMA Effective June 2007
Short Identifier=FEMAeff0607
Geom File=g01
Flow File=f03
Std Step Tol= 0.003
Critical Tol= 0.003
Max Error Tol= 0.1
Encroach Param=-1 ,0,0, 0

--- Q101-00-00.f04 (steady flow) ---

Flow Title=Floodway
Version=Version 3.0.1  Mar 2001
Number of Profiles= 2
Profile Names=1PCT_100yr,1PCTFloodway_100yrFW
River Rch & RM=Q101-00-00,Q101-00-0002    ,2964.744
    1317    1317
River Rch & RM=Q101-00-00,Q101-00-0002    ,2915.534
    1354    1354
River Rch & RM=Q101-00-00,Q101-00-0002    ,2620.905
    1461    1461
River Rch & RM=Q101-00-00,Q101-00-0002    ,1810.962
    1499    1499
River Rch & RM=Q101-00-00,Q101-00-0002    ,1529.386
    1616    1616
Boundary for River Rch & Prof#=Q101-00-00,Q101-00-0002    , 1
Up Type= 0
Dn Type= 3
Dn Slope=1.19197E-03
DSS Import GetInterval= 0
DSS Import GetPeak= 0
DSS Import FillOption= 0

--- Q101-00-00.f03 (steady flow) ---

Flow Title=FEMA Effective June 2007
Version=Version 3.0.1  Mar 2001
Number of Profiles= 4
Profile Names=10PCT_10yr,2PCT_50yr,1PCT_100yr,0.2PCT_500yr
River Rch & RM=Q101-00-00,Q101-00-0002    ,2964.744
     761    1127    1317    1873
River Rch & RM=Q101-00-00,Q101-00-0002    ,2915.534
     782    1159    1354    1925
River Rch & RM=Q101-00-00,Q101-00-0002    ,2620.905
     843    1250    1461    2077
River Rch & RM=Q101-00-00,Q101-00-0002    ,1810.962
     866    1283    1499    2132
River Rch & RM=Q101-00-00,Q101-00-0002    ,1529.386
     933    1383    1616    2297
Boundary for River Rch & Prof#=Q101-00-00,Q101-00-0002    , 1
Up Type= 0
Dn Type= 3
Dn Slope=1.19197E-03
DSS Import GetInterval= 0
DSS Import GetPeak= 0
DSS Import FillOption= 0

--- Q101-00-00.g01 (geometry) ---

Geom Title=Q101-00-00 June 2007
Version=Version 3.0.1  Mar 2001

River Reach=Q101-00-00      ,Q101-00-0002
Reach XY= 30
     3252544.884    13829976.601     3252704.789    13830007.572
     3252817.678    13829995.689     3252885.726    13829936.128
     3253060.571    13829823.509     3253208.264    13829753.436
     3253305.289    13829722.172     3253357.035    13829720.016
     3253374.284    13829730.797     3253481.011    13829744.811
     3253585.582    13829783.621     3253629.722    13829786.914
     3253787.634     13829982.32     3253828.434    13830017.181
     3253887.654    13830020.399     3253932.069    13830051.297
     3254073.682    13830048.078     3254123.246    13830080.263
     3254238.467    13830087.343     3254412.908    13830198.702
     3254497.232    13830222.519     3254538.429    13830221.232
      3254606.66    13830248.911     3254672.922    13830260.087
     3254815.217    13830210.933     3254845.471    13830194.197
     3254887.955    13830127.252     3254962.623    13830091.206
     3255097.799    13830079.619     3255211.089    13830095.711

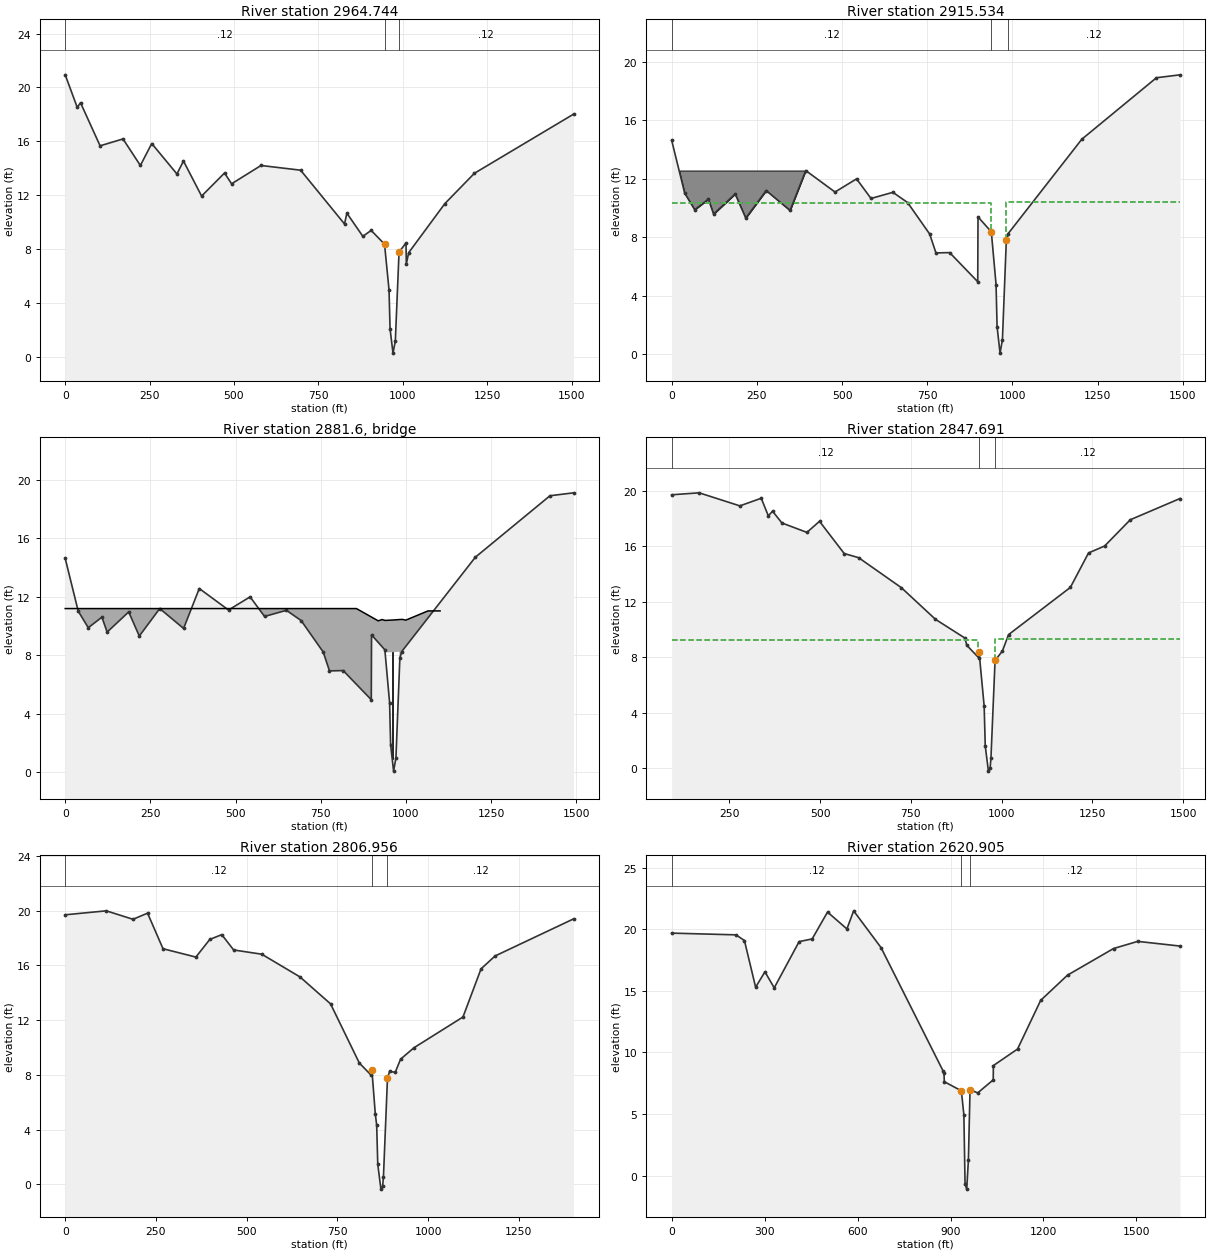
Type RM Length L Ch R = 1 ,2964.744,54.31,49.21,48.95
BEGIN DESCRIPTION:
xsec 4/4 of 432s1- 432s1u.  Surveyed section.
500 yr flow in LOB is effective, it will re-enter channel through u/s swale.
Bank Station offset =      4029
(Previously RS 3106, 56.53, 49.21, 48.95)
END DESCRIPTION:
XS GIS Cut Line= 6
     3252433.804    13830945.987     3252467.516    13830782.048
      3252557.81    13830046.453      3252575.92    13829946.039
     3252598.119    13829625.834     3252619.753    13829452.761
#Sta/Elev= 30
       0   20.94   35.67   18.52   45.33   18.87  103.33   15.67  171.22   16.18
  222.68   14.21  256.38   15.84  331.02   13.58  350.38   14.54  404.09   11.94
  471.98   13.65  492.92   12.85  580.06   14.21  697.42   13.86  827.44    9.87
  834.49   10.67  881.74    8.95  906.43    9.39     946    8.37  959.37    4.97
  962.39    2.09   971.1     .28  978.03    1.19     989    7.78 1009.68    8.46
 1010.56     6.9 1017.62    7.74  1124.8   11.38 1212.26   13.63 1505.95   18.02
#Mann= 3 , 0 , 0
       0     .12       0     946    .045       0     989     .12       0
Bank Sta=946,989
XS Rating Curve= 0
Exp/Cntr=.5,.3

Type RM Length L Ch R = 1 ,2915.534,68.56,67.84,68.77
BEGIN DESCRIPTION:
xsec 3/4 of 432s1; Copy of 432s1u; Adjusted elevations down 0.2 ft between bank stations based on nearest surveyed sections.
Bank Station offset =      4036
(Previously RS 3057, 68.77, 67.84, 68.76)
Block in LOB is a ditch that runs along the XS
END DESCRIPTION:
XS GIS Cut Line= 6
     3252456.363    13830939.262     3252494.341    13830803.669
     3252569.229    13830349.795     3252598.364    13830122.385
     3252634.176    13829863.808      3252677.79    13829465.686
#Sta/Elev= 30
       0   14.62   38.22   11.01   67.68    9.88  107.65    10.6  123.04    9.58
  186.28   10.96  217.41    9.31  277.41   11.19  347.42    9.83   393.4   12.56
  479.27   11.09  542.54   11.99  584.95   10.65  649.18   11.07  692.31   10.37
  757.07    8.22   775.5    6.93  815.71    6.95  898.14    4.96  898.94    9.39
     938    8.37  951.88    4.77   954.9    1.89  963.61     .08  970.54     .99
     982    7.78  987.47    8.25 1203.58    14.7 1422.51    18.9 1491.66    19.1
#Mann= 3 ,-1 , 0
       0     .12       0     938    .025       0  987.47     .12       0
#XS Ineff= 2 , 0
       0     937   10.35     982       0   10.41
Permanent Ineff=
       F       F
#Block Obstruct= 2 , 0
       0   393.4   12.56               0
Bank Sta=938,982
XS Rating Curve= 0
Exp/Cntr=.5,.3

Type RM Length L Ch R = 3 ,2881.6  ,,,
BEGIN DESCRIPTION:
432s1   FM 2354 (Tri-City Beach Road)
END DESCRIPTION:
Bridge Culvert--1,0,-1,-1, 0
Deck Dist Width WeirC Skew NumUp NumDn MinLoCord MaxHiCord MaxSubmerge Is_Ogee
17,34,2.6,0, 13, 13, , , .95, 0, 0,0,,
       0  854.61  918.61  929.61  938.61  938.61  963.61  980.61  980.61  989.61
  999.61 1064.61    1100
   11.19   11.19   10.35   10.44   10.38   10.38   10.41   10.44   10.44   10.45
    10.4   11.03   11.03
       0       0       0       0       0    8.18    8.21    8.24       0       0
       0       0       0
     791  854.68  918.68  929.68  938.68  938.68  963.68  980.68  980.68  989.68
  999.68 1064.68    1091
   11.19   11.19   10.35   10.44   10.38   10.38   10.41   10.44   10.44   10.45
    10.4   11.03   11.03
       0       0       0       0       0    8.18    8.21    8.24       0       0
       0       0       0
Pier Skew, UpSta & Num, DnSta & Num=  ,959.61, 4 ,959.68, 4 , 3 , 3 , 0 ,,
     1.2     1.2       2       2
       0     6.2     6.2    8.99
     1.2     1.2       2       2
       0     6.2     6.2    8.99
BR Coef=-1 , 0 , 0 ,, 0 ,,,.8,0,,0,
WSPro=,,,, 1 ,,,, 0 ,,,, 0 ,,,,-1 ,-1 ,-1 , 0 , 0 , 0 , 0 , 0
BC Design=,, 0 ,, 0 ,,,,,,

Type RM Length L Ch R = 1 ,2847.691,41.33,40.74,40.17
BEGIN DESCRIPTION:
xsec 2/4 of 432s1; Copy of 432s1u; Adjusted elevations down 0.47 ft between bank stations based on nearest surveyed sections.
Channel Manning's n changed from 0.025 to 0.03 as the 100yr WSEL changed between the 4flood and the floodway
Bank Station offset =      4127
(Previously RS 2989, 41.22, 40.74, 40.17)
END DESCRIPTION:
XS GIS Cut Line= 4
     3252571.546    13830863.903     3252678.556    13830043.324
     3252713.501    13829802.511     3252753.021    13829475.222
#Sta/Elev= 30
      91   19.71  166.82   19.85  278.84   18.91  337.78   19.46  357.32   18.19
   368.9   18.53  394.67   17.68  463.66      17  498.29    17.8  566.31   15.48
  606.14   15.18  723.82   13.02  817.86   10.74  899.01    9.39  904.07    8.87
  937.42    7.96     938    8.37  951.95     4.5  954.97    1.62  963.68    -.19
   968.3     .01  970.61     .72     982    7.78 1002.26    8.46 1019.19    9.64
 1189.49   13.04  1239.5   15.52 1283.82   16.02  1354.5   17.91 1491.53   19.44
#Mann= 3 , 0 , 0
      91     .12       0     938     .03       0     982     .12       0
#XS Ineff= 2 , 0
       0     936    9.28     982       0    9.32
Permanent Ineff=
       F       F
Bank Sta=938,982
XS Rating Curve= 0
Exp/Cntr=.5,.3

Type RM Length L Ch R = 1 ,2806.956,210.54,186.05,160.1
BEGIN DESCRIPTION:
xsec 1/4 of 432s1; Copy of 432s1u; Adjusted invert elevation 0.63 ft down between bank stations based on nearest surveyed sections.
Bank Station offset =      4130
(Previously 2949, 209.22, 186.05, 160.14)
END DESCRIPTION:
XS GIS Cut Line= 4
     3252618.204    13830867.236     3252732.411     13829945.28
     3252742.078    13829870.712     3252781.631    13829476.282
#Sta/Elev= 30
       0    19.7  113.23   19.99  186.89   19.37  226.92   19.82  269.46   17.22
  360.06   16.61   398.4    17.9  431.37   18.25  464.09   17.13  541.57   16.82
  646.83   15.16  731.13   13.19  810.31    8.87  843.66    7.96     845    8.37
  854.41    5.14  858.19    4.34  861.21    1.46  869.92    -.35  874.54    -.15
  876.85     .56     888    7.78  893.78    8.25  909.42    8.19  924.08    9.15
  961.37    9.99 1095.98   12.23  1145.8   15.75 1184.37   16.69  1400.6    19.4
#Mann= 3 , 0 , 0
       0     .12       0     845    .045       0     888     .12       0
Bank Sta=845,888
XS Rating Curve= 0
Exp/Cntr=.3,.1

Type RM Length L Ch R = 1 ,2620.905,737.47,809.94,873.09
BEGIN DESCRIPTION:
432v1
Bank Station offset =      4048
(Previously 2762, 837.02, 951.49, 1000.5)
END DESCRIPTION:
XS GIS Cut Line= 4
     3252894.823    13830870.569     3252929.975    13829992.308
     3252832.492    13829866.215     3252861.006    13829264.562
#Sta/Elev= 30
       0   19.68  207.63   19.54  234.81   19.08  270.97   15.29  300.99   16.54
  331.02   15.24  411.35   18.99  453.47   19.21  503.06   21.39  565.64   20.02
  587.29   21.49  675.58   18.51  875.47    8.52  878.96    8.31  879.97    7.62
     935    6.88  943.15    4.91  946.91    -.68  952.27    -1.1   957.7    1.25
     963    6.97  987.72    6.71 1037.84    7.77 1038.35    8.93 1116.31   10.27
 1190.93   14.22 1277.66   16.27 1426.23   18.43 1504.31   19.01 1640.67   18.63
#Mann= 3 , 0 , 0
       0     .12       0     935    .045       0     963     .12       0
Bank Sta=935,963
XS Rating Curve= 0
Exp/Cntr=.3,.1

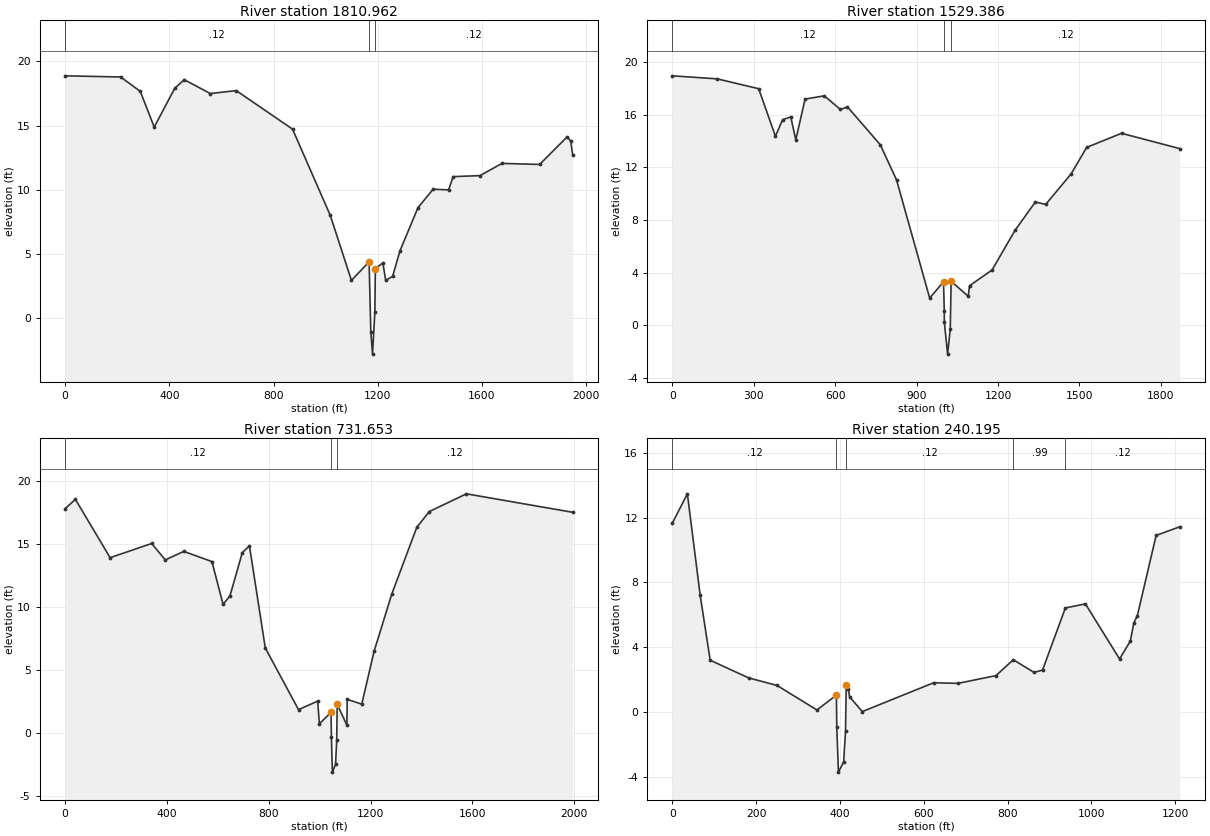
Type RM Length L Ch R = 1 ,1810.962,290.08,281.58,267.7
BEGIN DESCRIPTION:
432v2
Bank Station offset =      3820
(Previously 1811, 290.08, 281.56, 282.77)
END DESCRIPTION:
XS GIS Cut Line= 6
     3253274.757    13830907.229     3253575.585    13829849.457
     3253621.248    13829798.007     3253638.703     13829778.34
     3253698.867    13829710.553     3253841.533    13829062.448
#Sta/Elev= 30
       0   18.87  212.88   18.78  288.41   17.66  341.88   14.88  420.88    17.9
  457.09   18.57  557.38   17.49   656.8   17.72  872.99   14.72 1018.01       8
  1099.2    2.94    1167    4.39 1173.55   -1.05 1180.18    -2.8 1189.19     .48
    1191    3.86 1219.92     4.3 1230.69    2.94 1257.41    3.26 1285.44    5.24
 1354.69     8.6 1412.64   10.04 1472.32    9.99 1489.81   11.02 1592.99    11.1
 1676.99   12.05  1821.8   11.97 1927.59   14.12 1941.34   13.78 1949.06   12.67
#Mann= 3 , 0 , 0
       0     .12       0    1167    .045       0    1191     .12       0
Bank Sta=1167,1191
XS Rating Curve= 0
Exp/Cntr=.3,.1

Type RM Length L Ch R = 1 ,1529.386,788.34,797.73,759.88
BEGIN DESCRIPTION:
432v3
Bank Station offset =      3986
(Previously 1529, 797.03, 797.73, 762.91)
END DESCRIPTION:
XS GIS Cut Line= 4
     3253371.407    13830917.227     3253776.799    13830058.647
     3253853.164    13829935.115     3254175.347    13829229.355
#Sta/Elev= 30
       0   18.97  165.11   18.74  317.84   17.99  379.49   14.38   406.1   15.63
  436.09   15.85  454.51    14.1   488.8    17.2  559.51   17.45  619.14   16.41
  644.98   16.61  765.92   13.73  825.76   11.06  947.97    2.07     999    3.31
 1001.74    1.07 1002.07     .22 1014.01   -2.19  1023.8    -.28    1027    3.35
 1089.95    2.21  1094.7    3.01 1177.55     4.2 1262.45    7.22 1337.38    9.38
 1375.35    9.19 1469.37   11.52 1526.55   13.53 1654.96    14.6 1870.53   13.43
#Mann= 3 , 0 , 0
       0     .12       0     999    .045       0    1027     .12       0
Bank Sta=999,1027
XS Rating Curve= 0
Exp/Cntr=.3,.1

Type RM Length L Ch R = 1 ,731.653 ,468.19,491.46,511.04
BEGIN DESCRIPTION:
432v4  The ROB length, compared to the channel length, differs by more than 20 feet.
Bank Station offset =      3950
(Previously 732, 468.19, 491.46, 560.66)
END DESCRIPTION:
XS GIS Cut Line= 6
     3253841.533     13831003.65     3254532.279    13830280.106
     3254551.183    13830211.889      3254561.15    13830175.919
     3254630.364    13829817.842     3254372.306    13829364.448
#Sta/Elev= 30
       0   17.82   40.17   18.56  176.66   13.92  340.06   15.05   393.5   13.74
  466.03   14.42  576.81   13.61  620.53    10.2  647.78   10.89  696.26   14.33
  724.22   14.86  786.43    6.74  916.99    1.83  992.52    2.51  998.91      .7
    1045    1.62 1046.22    -.34 1050.19   -3.14  1062.6   -2.51 1067.04    -.62
    1069    2.26 1107.12      .6 1108.44    2.65 1165.58    2.27 1214.29    6.49
 1283.63   11.03 1381.74   16.33 1430.99   17.59 1576.88      19 1994.83   17.53
#Mann= 3 , 0 , 0
       0     .12       0    1045    .045       0    1069     .12       0
Bank Sta=1045,1069
XS Rating Curve= 0
Exp/Cntr=.3,.1

Type RM Length L Ch R = 1 ,240.195 ,256.27,240.2,613.89
BEGIN DESCRIPTION:
Copy of xs 432v4. Channel inverts adjusted based on slope.
Bank Station offset =      4603.82
END DESCRIPTION:
XS GIS Cut Line= 4
     3254979.715    13830500.449     3254982.844    13830333.078
     3254943.181    13829291.932     3254941.188    13829292.579
#Sta/Elev= 30
       0   11.67   35.64   13.47   66.27    7.19   90.08    3.19  181.78     2.1
  249.68    1.63   344.9   .1169  391.28  1.0369  392.21  -.9231  396.18 -3.7231
  408.59 -3.0931  413.03 -1.2031  414.78  1.6769  419.63  1.4269   422.8   .9269
  453.11   .0169  623.54     1.8   681.3    1.76  772.15    2.24  813.47    3.22
  862.83    2.44  883.25    2.58  937.75    6.42  985.59    6.67 1067.05    3.27
 1092.72    4.37 1101.34    5.51 1109.53    5.94 1154.33    10.9  1211.4   11.44
#Mann= 5 ,-1 , 0
       0     .12       0  391.28    .045       0  414.78     .12       0
  813.47     .99       0  937.75     .12       0
#Block Obstruct= 2 , 0
       0                    1020       0     4.5
Bank Sta=391.28,414.78
XS Rating Curve= 0
Exp/Cntr=.3,.1

Chan Stop Cuts=-1